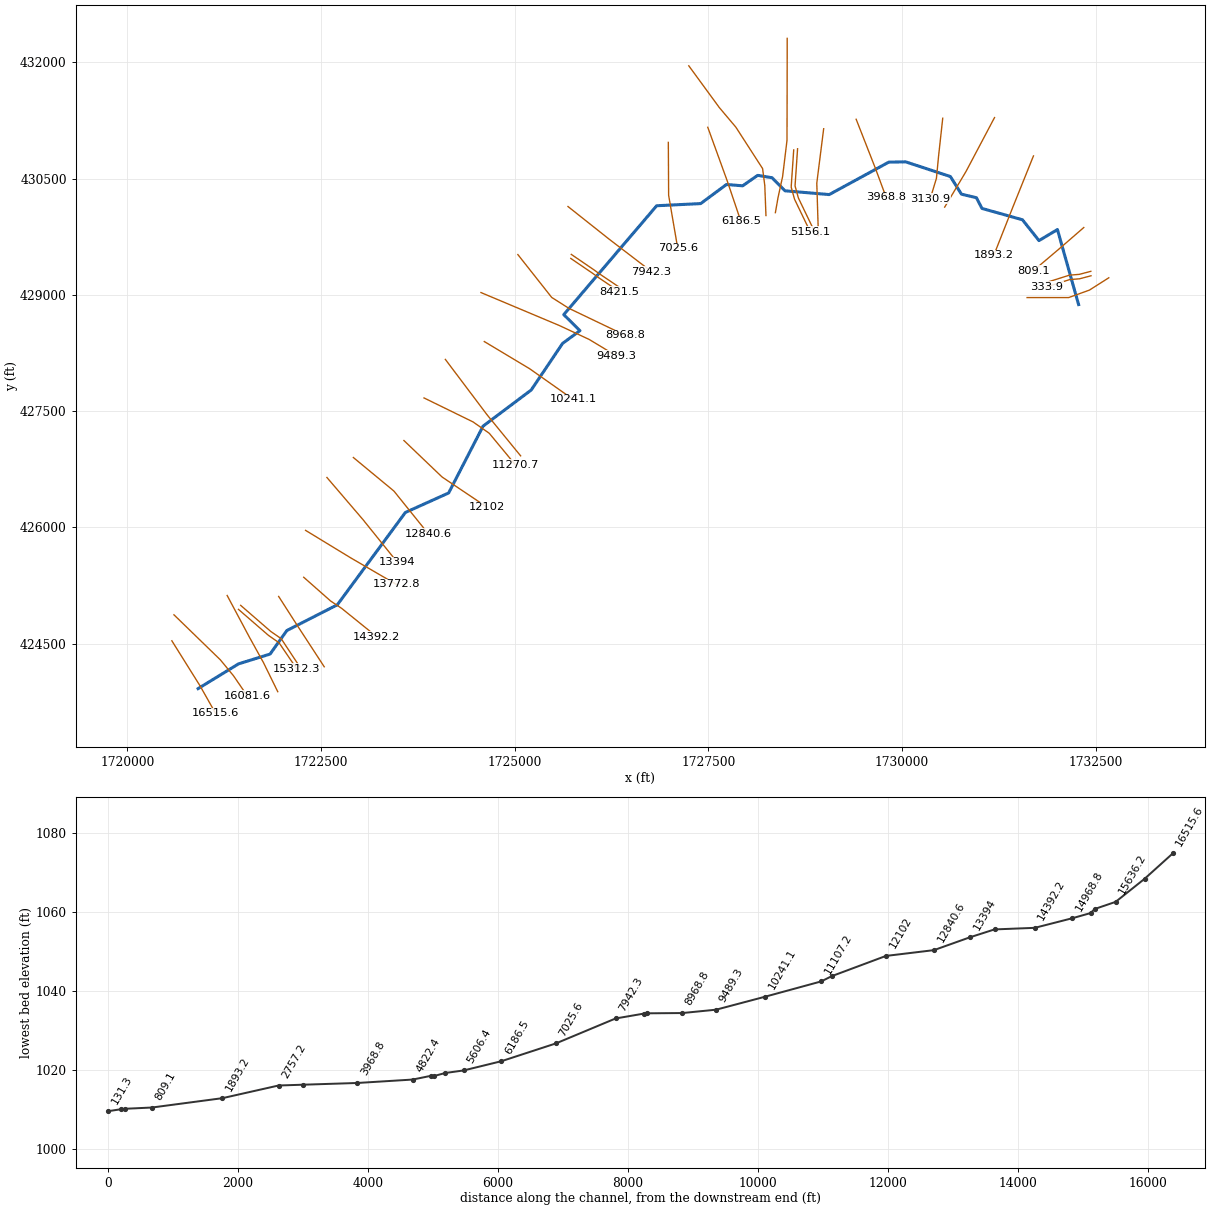
--- NFkWVaFork.prj (project) ---

Proj Title=NFkWVaFork
Current Plan=p01
Default Exp/Contr=0,0
English Units
Geom File=g01
Flow File=f01
Plan File=p01
BEGIN DESCRIPTION:
END DESCRIPTION:
DSS Export Rating Curves= 0
DSS Export Rating Curve Sorted= 0
DSS Export Volume Flow Curves= 0
DXF OffsetX= 0
DXF OffsetY= 0
DXF ScaleX= 0
DXF ScaleY= 0

--- NFkWVaFork.p01 (plan) ---

Plan Title=Floodplain
Program Version=4.00
Geom File=g01
Flow File=f01
K Sum by GR=0
Std Step Tol=0.01
Critical Tol=0.01
Num of Std Step Trials=20
Max Error Tol=0.3
Flow Tol Ratio=0.001
Split Flow NTrial=30
Split Flow Tol=0.02
Split Flow Ratio=0.02
Log Output Level=0
Friction Slope Method=1
Unsteady Friction Slope Method=2
Unsteady Bridges Friction Slope Method=1
Global Log Level=0
CheckData=False
Run HTab=0
Run UNet=0
Run PostProcess=0
UNET Theta=0
UNET Theta Warmup=0
UNET ZTol=0
UNET ZSATol=0
UNET MxIter=0
UNET MaxInSteps=0
UNET DtIC=0
UNET DtMin=0
UNET MaxCRTS=0
UNET WFStab=0
UNET SFStab=0
UNET WFX=0
UNET SFX=0
UNET DSS MLevel=0
UNET DZMax Abort=0
UNET Convert EG Bridges=0
UNET Use Existing IB Tables=0
UNET Froude Limit=0
UNET Froude Power=0
Write IC File=0
Echo Input=False
Echo Output=False
Write Detailed=0

--- NFkWVaFork.f01 (steady flow) ---

Flow Title=NFF Regression Equation
Program Version=4.10
Number of Profiles= 1
Profile Names=P100yr
River Rch & RM=NFkWVaFork,Main            ,16515.6
     919
River Rch & RM=NFkWVaFork,Main            ,13772.8
     963
River Rch & RM=NFkWVaFork,Main            ,11270.7
    1032
River Rch & RM=NFkWVaFork,Main            ,11107.2
    1254
River Rch & RM=NFkWVaFork,Main            ,9489.3
    1273
River Rch & RM=NFkWVaFork,Main            ,8968.8
    1441
River Rch & RM=NFkWVaFork,Main            ,5606.4
    1533
River Rch & RM=NFkWVaFork,Main            ,5322.1
    2324
River Rch & RM=NFkWVaFork,Main            ,131.3
    2424
Boundary for River Rch & Prof#=NFkWVaFork,Main            , 1
Up Type= 0
Dn Type= 3
Dn Slope=0.0025
DSS Import GetInterval= 0
DSS Import GetPeak= 0
DSS Import FillOption= 0

--- NFkWVaFork.g01 (geometry) ---

Geom Title=USGS 10m DEM
Program Version=4.10

River Reach=NFkWVaFork      ,Main
Reach XY= 30
     1720913.463      423920.159     1721436.185      424239.588
     1721842.936      424365.776      1722059.95      424669.595
     1722710.991      425001.192     1723589.464      426192.164
     1724148.492        426443.9     1724592.682      427305.627
     1725214.464      427772.025     1725618.978       428372.72
     1725843.431      428537.319     1725634.603      428744.248
     1726834.256      430148.761     1727401.964      430176.539
     1727735.297      430423.067     1727943.631      430405.706
     1728137.614      430540.733     1728323.839      430509.873
     1728490.505       430341.47     1729061.463      430292.814
     1729830.783      430711.262     1730049.533      430714.734
     1730625.922      430525.498     1730768.283      430298.067
     1730961.639      430252.604     1731033.908      430114.039
     1731555.908      429968.076     1731770.019      429699.109
     1732007.867       429841.47     1732281.106      428874.287

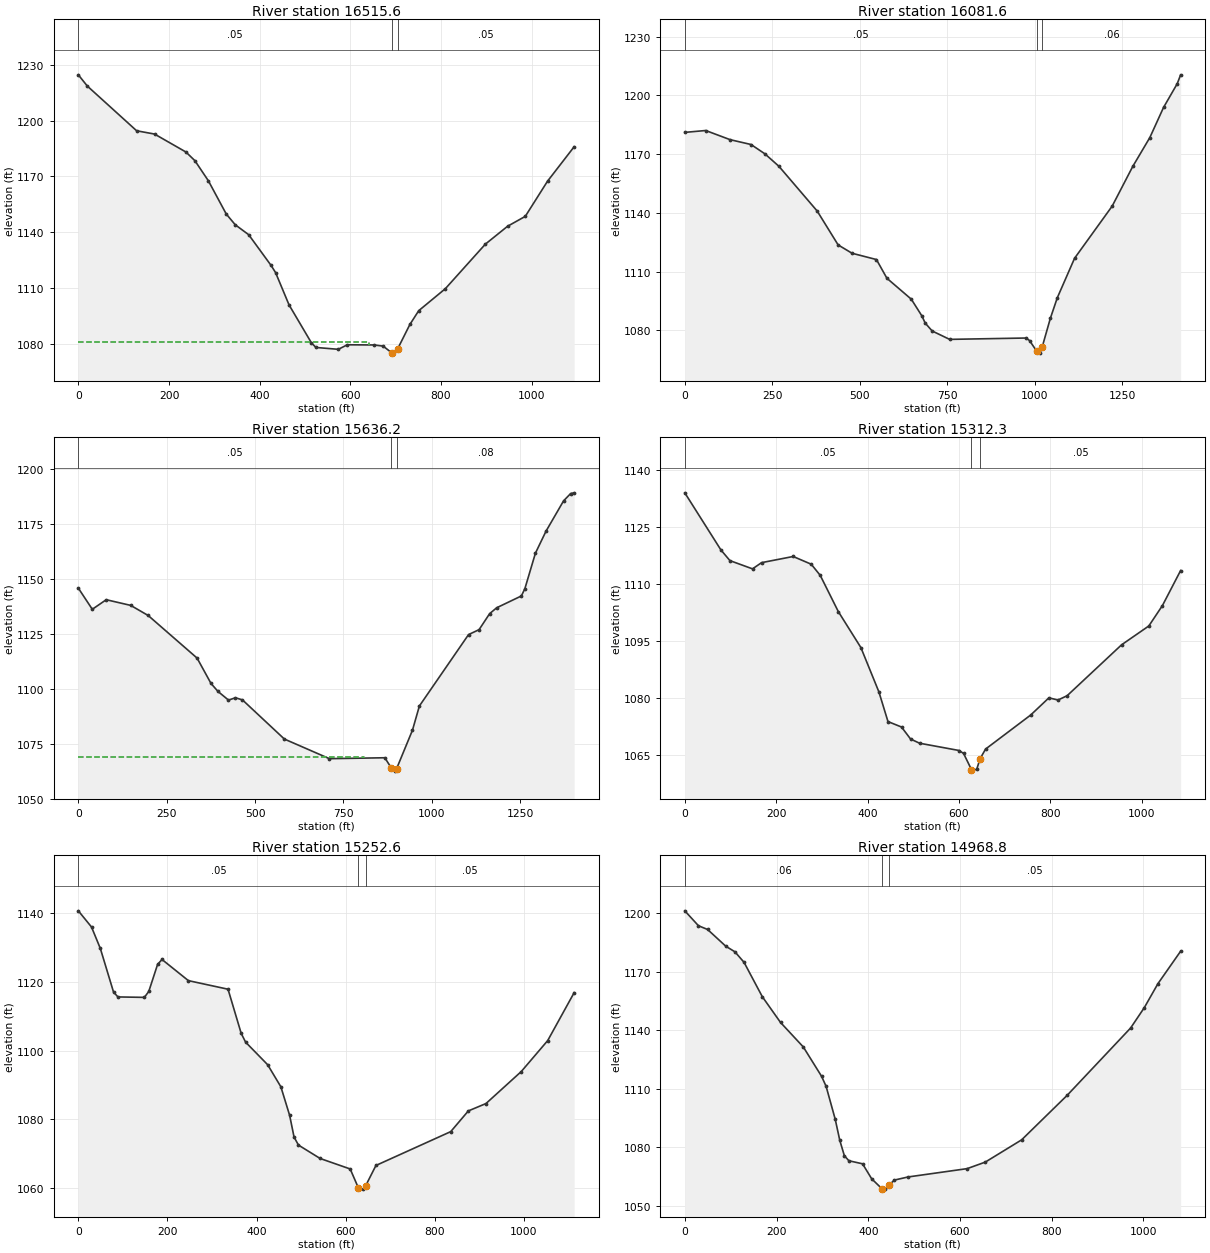
Type RM Length L Ch R = 1 ,16515.6 ,430.2,434,437.9
XS GIS Cut Line= 3
     1720574.818      424536.966     1720937.221      423958.871
      1721139.79      423600.825
#Sta/Elev= 30
       0 1224.68    19.8 1218.64   128.6 1194.57   168.1  1192.8   237.3 1183.14
   257.1 1178.48   286.8 1167.67   326.3 1149.76   346.1 1143.98   375.8 1138.62
   425.2 1122.08   435.1 1118.24   464.8 1100.85   514.2 1080.41   524.1 1077.94
   573.5 1076.94   593.3 1079.38   652.6 1079.28   672.4 1078.66  691.861074.953
   692.1 1074.89  704.391077.198   731.3  1090.3   750.9 1097.75   809.6 1109.58
   897.8 1133.54   946.8 1143.17   985.9  1148.5  1034.9 1167.41  1093.7 1185.98
#Mann= 3 , 0 , 0
       0     .05       0  691.86    .045       0  704.39     .05       0
#XS Ineff= 2 , 0
          641.92 1081.02
Permanent Ineff=
       F       F
Bank Sta=691.86,704.39
XS Rating Curve= 0 ,0
Exp/Cntr=0.3,0.1

Type RM Length L Ch R = 1 ,16081.6 ,448.9,445.4,441.3
XS GIS Cut Line= 4
     1720601.831      424872.633     1721202.145       424290.35
     1721372.284      424083.753     1721549.368       423825.94
#Sta/Elev= 30
       0 1181.11    59.7 1182.07   129.4  1177.4   189.2 1174.93     229 1170.15
   268.8 1163.83   378.3 1140.96   438.1 1123.68   477.9 1119.42   547.6 1116.21
   577.5 1106.66   647.2 1095.97     677 1087.56     687 1083.76   706.9 1079.74
   756.7 1075.47   975.1 1076.16     985 1074.87    1006  1069.3  1014.7 1068.45
    1021 1071.47  1044.5 1086.22  1064.3 1096.68  1113.7 1116.87  1221.2  1143.5
  1279.9 1163.72  1328.8 1178.49  1367.9 1193.84    1407 1205.96  1416.7 1210.49
#Mann= 3 , 0 , 0
       0     .05       0    1006    .045       0    1021     .06       0
Bank Sta=1006,1021
XS Rating Curve= 0 ,0
Exp/Cntr=0.3,0.1

Type RM Length L Ch R = 1 ,15636.2 ,313.5,323.9,334
XS GIS Cut Line= 4
     1721288.951      425121.513     1721577.579      424581.149
     1721757.701      424255.628     1721942.163      423880.194
#Sta/Elev= 30
       0  1145.8    39.5 1136.18      79 1140.53   148.2 1137.95   197.6 1133.36
     336    1114   375.5 1102.45   395.2 1098.83   424.9  1094.9   444.6 1095.96
   464.4 1094.99     583 1077.19   710.5 1068.27   867.2 1068.69   885.3 1064.15
   896.5 1062.61   900.3 1063.61   945.5 1081.23   965.1 1092.23  1104.2 1124.68
    1134 1126.93  1163.9  1134.2  1183.8 1136.87  1253.6 1142.24  1263.5 1145.53
  1293.4 1161.69  1323.3 1171.67  1373.1 1185.48    1393 1188.78    1403 1189.12
#Mann= 3 , 0 , 0
       0     .05       0   885.3    .045       0   900.3     .08       0
#XS Ineff= 2 , 0
          809.36 1069.24
Permanent Ineff=
       F       F
Bank Sta=885.3,900.3
XS Rating Curve= 0 ,0
Exp/Cntr=0.3,0.1

Type RM Length L Ch R = 1 ,15312.3 ,59.5,59.7,59.6
XS GIS Cut Line= 4
     1721435.164      424942.077     1721823.619      424605.706
     1721958.168       424512.39     1722187.389      424175.333
#Sta/Elev= 30
       0 1133.97      79 1118.96    98.8 1116.14   148.2 1113.98     168 1115.61
   237.2 1117.23   276.7  1115.2   296.4 1112.27     336 1102.74   385.4 1093.28
   424.9  1081.6   444.7 1073.82   474.3 1072.39   494.1 1069.24   513.8 1068.13
   600.5 1066.21   610.2 1065.43  627.321061.217   629.4 1060.79   639.1 1061.33
   646.1 1064.01   658.3 1066.59   757.1 1075.55   796.9 1080.06   816.8 1079.49
   836.7 1080.61     956 1094.01  1015.6 1098.96  1045.4 1104.33  1085.2 1113.54
#Mann= 3 , 0 , 0
       0     .05       0  627.32    .045       0   646.1     .05       0
Bank Sta=627.32,646.1
XS Rating Curve= 0 ,0
Exp/Cntr=0.3,0.1

Type RM Length L Ch R = 1 ,15252.6 ,292.7,283.7,275
XS GIS Cut Line= 4
     1721463.376      424994.161     1721851.831      424657.789
     1721986.379      424564.473     1722226.451      424201.374
#Sta/Elev= 30
       0 1140.55    29.6 1135.85    49.4 1129.62      79 1116.98    88.9 1115.56
   148.2 1115.43   158.1 1117.15   177.9    1125   187.8 1126.43     247 1120.29
     336  1117.8   365.6 1104.96   375.5 1102.43   424.9 1095.89   454.6 1089.48
   474.3 1081.18   484.2 1074.89   494.1 1072.56   542.8 1068.67   610.2 1065.63
  628.531060.152   639.1 1059.78   644.8 1060.73     668 1066.65   835.9 1076.47
   875.4 1082.48     915 1084.62   994.2 1093.91  1053.5 1102.89  1112.9 1116.81
#Mann= 3 , 0 , 0
       0     .05       0  628.53    .045       0   644.8     .05       0
Bank Sta=628.53,644.8
XS Rating Curve= 0 ,0
Exp/Cntr=0.3,0.1

Type RM Length L Ch R = 1 ,14968.8 ,565.7,576.6,585.3
XS GIS Cut Line= 3
     1721953.827      425109.178     1722190.055      424741.143
     1722541.935       424202.06
#Sta/Elev= 30
       0 1201.37    29.8 1193.71    49.7 1191.79    89.4 1183.19   109.3 1180.33
   129.2 1174.92     169 1157.28   208.7 1144.06   258.4 1131.46   298.2 1116.41
   308.1 1111.25     328 1094.33   337.9 1083.54   347.9 1075.62   357.8 1073.03
   387.6 1071.46   407.5 1063.75   429.8 1058.68   437.3 1058.46   444.8  1060.5
   457.1 1063.11   486.8 1064.71   615.6 1068.98   655.2 1072.34   734.4 1083.76
   833.5 1106.58   972.1 1141.21  1001.9 1151.65  1031.6 1163.96  1081.1 1180.62
#Mann= 3 , 0 , 0
       0     .06       0   429.8    .045       0   444.8     .05       0
Bank Sta=429.8,444.8
XS Rating Curve= 0 ,0
Exp/Cntr=0.3,0.1

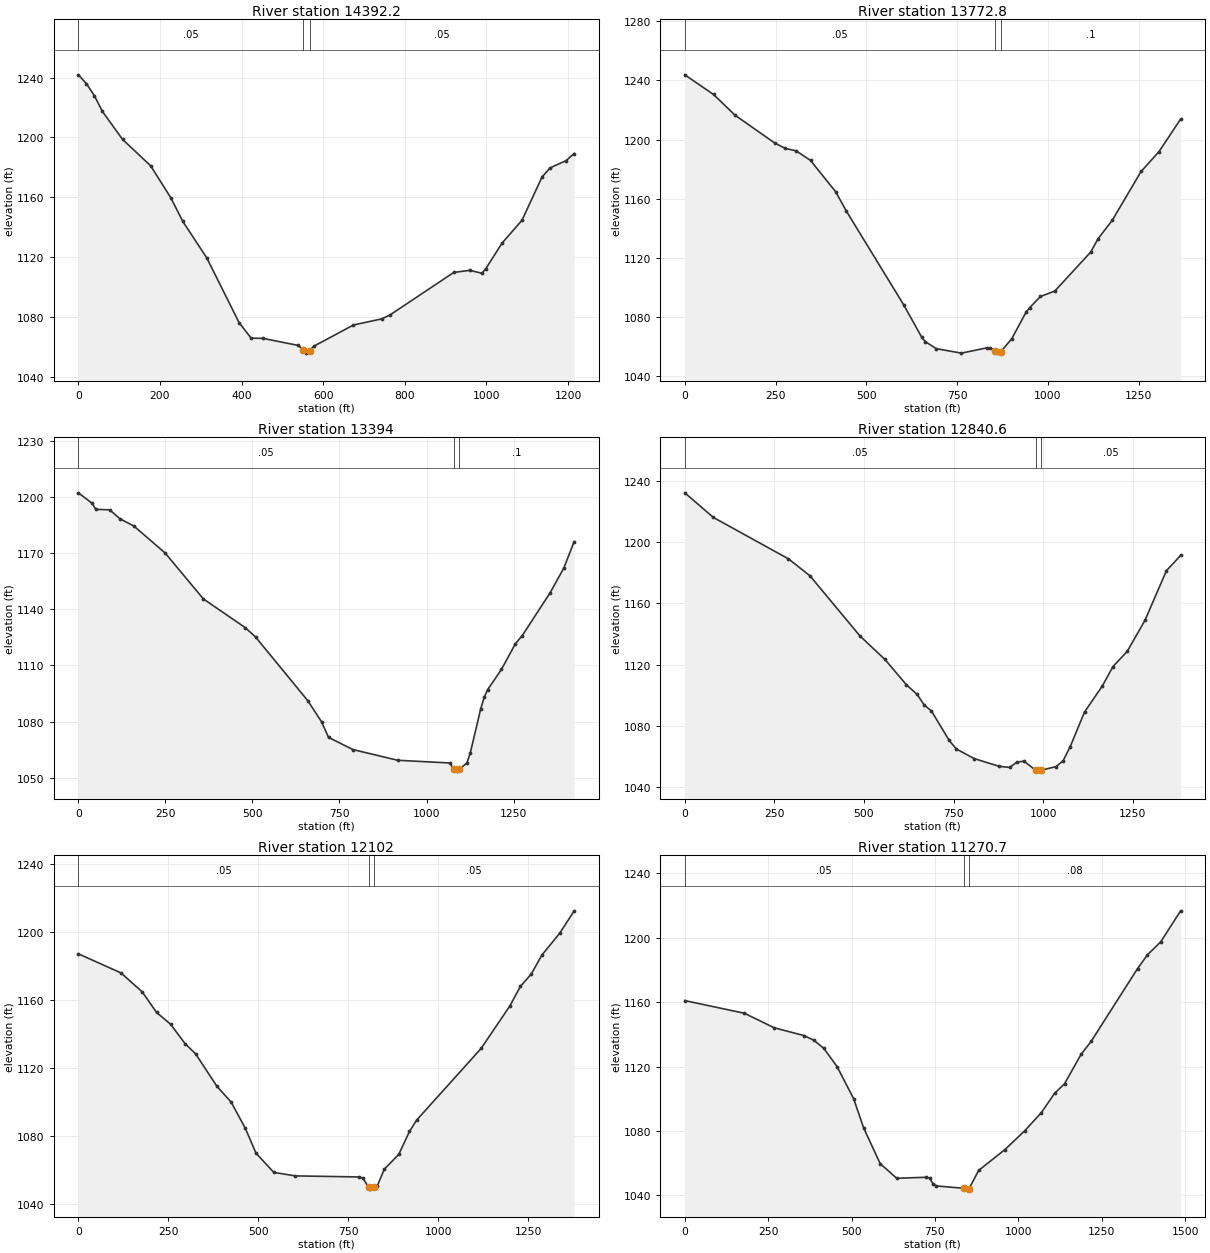
Type RM Length L Ch R = 1 ,14392.2 ,618.5,619.4,620.5
XS GIS Cut Line= 4
     1722277.178      425356.574       1722624.4      425050.584
     1722767.629      424955.098     1723219.018      424590.515
#Sta/Elev= 30
       0 1241.81    19.7    1236    39.4 1227.87    59.1 1217.35   108.3 1198.74
   177.2  1181.1   226.5  1159.8     256 1143.97   315.1 1119.46   393.9 1076.44
   423.4 1066.05     453 1065.85   539.3 1061.16   551.6 1057.92   558.4 1056.03
   566.6 1057.75   577.6  1060.7   674.3  1074.8   743.1 1078.88   762.8 1081.32
   920.2  1109.9   959.5  1111.3     989 1109.34   998.8 1112.45  1038.2 1129.37
  1087.3  1144.7  1136.5 1173.64  1156.2 1179.67  1195.5 1184.57  1215.2 1189.26
#Mann= 3 , 0 , 0
       0     .05       0   551.6    .045       0   566.6     .05       0
Bank Sta=551.6,566.6
XS Rating Curve= 0 ,0
Exp/Cntr=0.3,0.1

Type RM Length L Ch R = 1 ,13772.8 ,387.1,378.8,370.3
XS GIS Cut Line= 3
     1722301.369        425961.5     1722884.333      425606.652
     1723474.695      425263.838
#Sta/Elev= 30
       0 1243.82    79.1 1230.53   138.5  1216.5   247.3 1197.76   276.9 1194.04
   306.6 1192.43   346.2 1185.93   415.4 1164.74   445.1 1151.56   603.3 1088.04
   652.8  1066.2   662.7 1063.32   692.4 1058.65   761.6 1055.63   830.9 1059.16
   840.8 1059.21   855.4 1056.86   860.6 1055.64   870.4 1056.69   900.1 1065.34
   939.7 1083.31   949.6 1086.39   979.3 1093.94  1018.9 1097.63  1117.8 1124.02
  1137.6 1132.91  1177.2 1145.54  1256.3 1178.45  1305.8 1191.94  1365.2 1213.91
#Mann= 3 , 0 , 0
       0     .05       0   855.4    .045       0   870.4      .1       0
Bank Sta=855.4,870.4
XS Rating Curve= 0 ,0
Exp/Cntr=0.3,0.1

Type RM Length L Ch R = 1 ,13394   ,552.7,553.4,554.3
XS GIS Cut Line= 3
     1722576.965      426643.533     1723044.308      426097.806
     1723486.937      425548.582
#Sta/Elev= 30
       0 1202.14    39.9 1196.54    49.9 1193.32    89.8 1193.08   119.8 1188.26
   159.7  1184.4   249.5 1169.98   359.2  1145.5     479 1130.26   508.9 1125.22
   658.6 1091.31   698.5 1079.94   718.5 1071.65     788 1065.16   917.2 1059.42
  1066.2 1057.98    1078 1054.91  1086.1 1053.63    1093  1054.5  1115.9 1057.94
  1125.8 1063.51  1155.6 1086.92  1165.6  1093.1  1175.5 1097.14  1215.2 1107.92
    1255  1121.6  1274.8 1125.95  1354.3 1148.64  1394.1 1161.97  1423.9 1176.11
#Mann= 3 , 0 , 0
       0     .05       0    1078    .045       0    1093      .1       0
Bank Sta=1078,1093
XS Rating Curve= 0 ,0
Exp/Cntr=0.3,0.1

Type RM Length L Ch R = 1 ,12840.6 ,731.5,738.7,744.7
XS GIS Cut Line= 3
     1722918.557      426900.893     1723441.443        426468.9
     1723884.072      425919.676
#Sta/Elev= 30
       0 1232.28    79.8 1216.19   289.3 1189.12   349.1 1178.08   488.7 1138.75
   558.6 1123.36   618.4 1106.82   648.3 1100.53   668.3 1093.55   688.2 1089.72
   737.9 1070.42   757.7 1064.86   807.4 1058.59     877 1053.53   906.8  1052.8
   926.6 1056.28   946.5 1056.89   979.1 1050.95   986.2 1050.38   994.1 1050.95
  1035.9 1053.33  1055.8 1057.22  1075.6 1066.44  1115.4 1089.01  1165.1 1106.02
  1194.9 1118.76  1234.6 1128.65  1284.3 1149.05  1343.9 1181.34  1383.6 1191.36
#Mann= 3 , 0 , 0
       0     .05       0   979.1    .045       0   994.1     .05       0
#XS Ineff= 2 , 0
          946.51 1056.88
Permanent Ineff=
       F       F
Bank Sta=979.1,994.1
XS Rating Curve= 0 ,0
Exp/Cntr=0.3,0.1

Type RM Length L Ch R = 1 ,12102   ,831.7,831.3,830.8
XS GIS Cut Line= 3
     1723571.071      427120.357     1724063.879       426649.65
     1724642.296      426261.649
#Sta/Elev= 30
       0 1187.33   118.5 1176.12   177.8 1164.89   217.3 1152.89   256.8 1145.83
   296.3 1134.57   325.9 1128.51   385.2 1109.39   424.7 1100.12   464.2 1084.64
   493.8 1070.06   543.2 1058.76   602.5  1056.7     781 1056.07   790.9 1055.36
   807.1 1049.87   810.8 1048.91   822.1 1050.03   830.7 1050.77   850.6 1060.72
   890.4 1069.29   920.3 1082.82   940.2 1089.52  1119.3 1131.64  1198.9 1156.53
  1228.7  1168.2  1258.6  1175.4  1288.4 1186.61  1338.2 1199.57    1378 1212.63
#Mann= 3 , 0 , 0
       0     .05       0   807.1    .045       0   822.1     .05       0
Bank Sta=807.1,822.1
XS Rating Curve= 0 ,0
Exp/Cntr=0.3,0.1

Type RM Length L Ch R = 1 ,11270.7 ,169.6,163.4,157.3
XS GIS Cut Line= 4
      1723830.56      427669.719     1724463.916      427360.051
     1724672.574       427213.99     1725008.945      426808.174
#Sta/Elev= 30
       0 1160.98   178.7 1153.11   268.1 1144.09   357.5 1139.24   387.3  1136.3
     417 1131.27   456.8 1119.89   506.4 1099.95   536.2 1081.88   585.8 1059.68
   635.5 1050.55   724.6 1051.17   734.4 1050.68   744.2 1047.15     754 1045.78
   836.1 1044.34   842.2  1043.8     852 1043.99   881.3 1055.45   959.7 1068.35
  1019.4 1080.07  1069.1 1091.34  1108.9 1103.34  1138.7  1109.3  1188.4 1127.61
  1218.3 1135.57  1357.5 1180.84  1387.4 1189.43  1427.1  1197.5  1486.8 1216.78
#Mann= 3 , 0 , 0
       0     .05       0   836.1    .045       0     852     .08       0
Bank Sta=836.1,852
XS Rating Curve= 0 ,0
Exp/Cntr=0.3,0.1

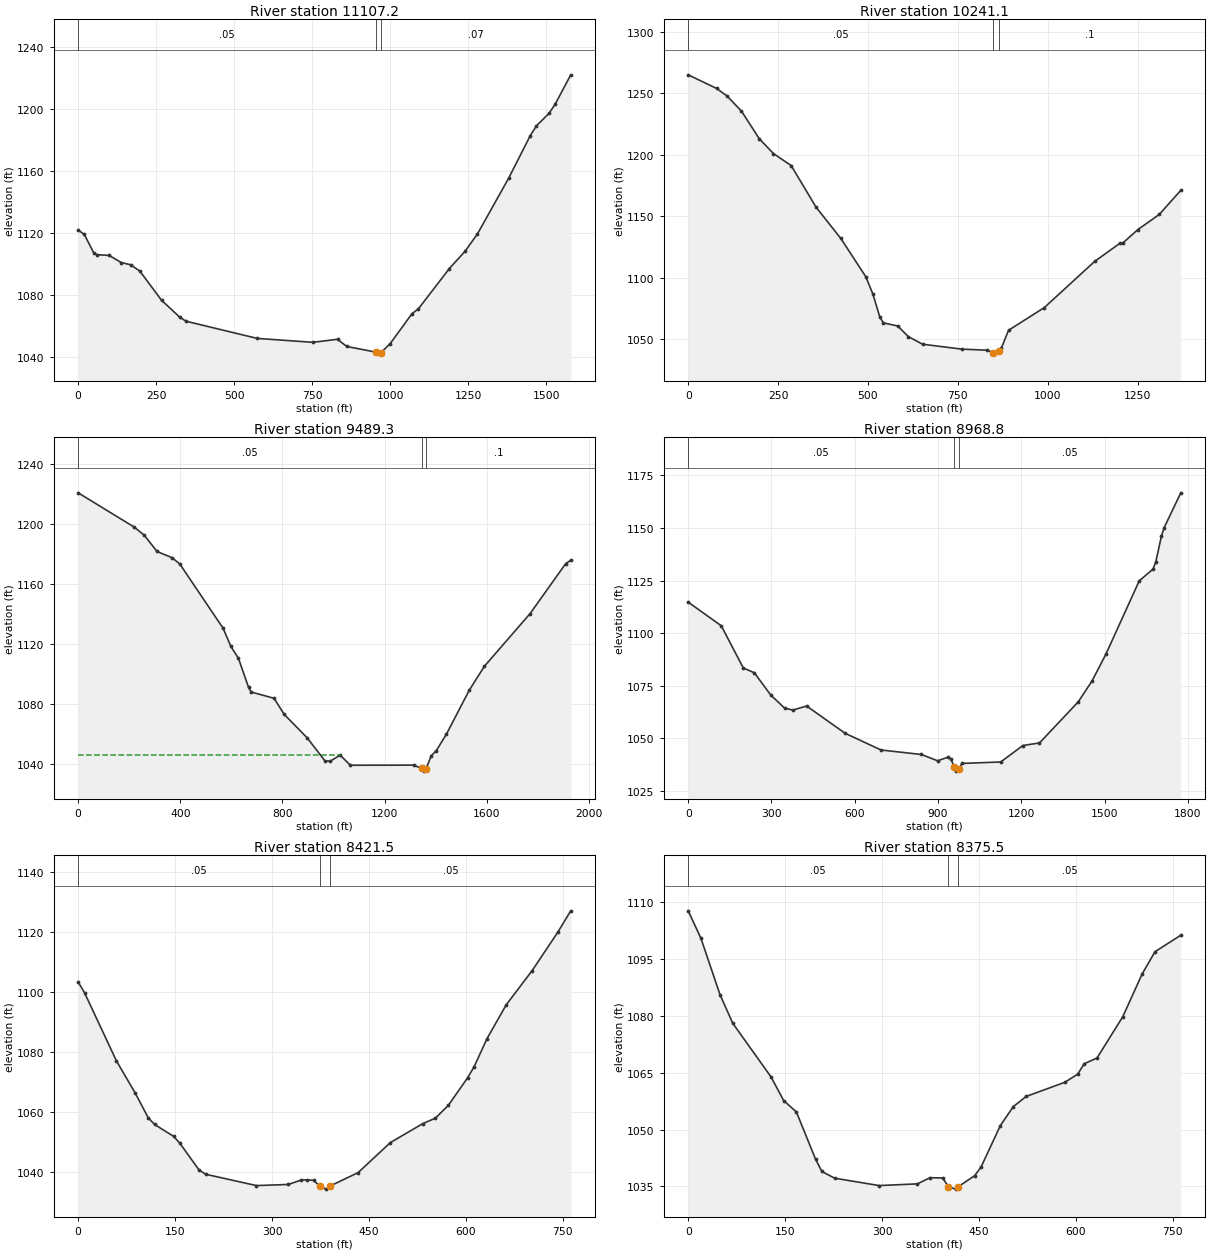
Type RM Length L Ch R = 1 ,11107.2 ,860,866.1,872.3
XS GIS Cut Line= 3
     1724105.737      428166.904     1724641.867      427455.537
     1725077.503      426922.665
#Sta/Elev= 30
       0 1121.89    19.8 1119.03    49.5 1107.34    59.4 1105.99      99 1105.55
   138.6 1100.88   168.3 1099.49     198 1095.36   267.2 1076.59   326.6 1065.49
   346.4 1063.02     574 1051.96   752.2 1049.44   831.4  1051.4   861.1 1046.74
   955.9 1043.04   960.6 1042.46   970.9  1042.8  1000.5 1048.66  1070.3 1067.94
  1090.3 1070.95    1190 1097.08  1239.9  1108.1  1279.8 1119.32  1379.6  1155.2
  1449.4 1182.86  1469.3 1189.22  1509.2 1197.15  1529.2 1203.14  1579.1 1222.08
#Mann= 3 , 0 , 0
       0     .05       0   955.9    .045       0   970.9     .07       0
Bank Sta=955.9,970.9
XS Rating Curve= 0 ,0
Exp/Cntr=0.3,0.1

Type RM Length L Ch R = 1 ,10241.1 ,747.5,751.8,755.9
XS GIS Cut Line= 3
     1724608.722      428396.934     1725193.272      428046.899
     1725756.431       427650.29
#Sta/Elev= 30
       0 1264.86      79  1253.8   108.6 1247.51   148.1 1235.34   197.5 1212.98
     237 1200.84   286.4 1191.07   355.5 1157.29   424.6 1131.78   493.7 1100.82
   513.5 1086.75   533.2 1067.74   543.1 1063.13   582.6 1060.64   612.2 1052.03
   651.7 1045.83   761.2 1041.82   831.1 1040.96   848.8 1038.98     851 1038.57
   863.8 1039.96     871 1042.62     891 1057.13   990.8 1075.67  1130.6 1113.16
  1200.4 1127.81  1210.4  1128.5  1250.4 1138.94  1310.2 1151.31  1370.1 1170.94
#Mann= 3 , 0 , 0
       0     .05       0   848.8    .045       0   863.8      .1       0
Bank Sta=848.8,863.8
XS Rating Curve= 0 ,0
Exp/Cntr=0.3,0.1

Type RM Length L Ch R = 1 ,9489.3  ,523.5,520.5,518.7
XS GIS Cut Line= 4
     1724566.023      429028.796      1725576.44      428604.317
     1725961.857      428424.629     1726311.466      428214.213
#Sta/Elev= 30
       0 1221.06   219.2 1198.21     259 1192.76   308.9  1181.9   368.6 1177.69
   398.5 1173.45   567.9 1130.58   597.8 1118.62   627.7 1110.57   667.5 1091.13
   677.5 1088.11   767.2  1083.9     807 1073.17   896.7 1057.54   966.4 1042.17
   986.4  1041.9  1026.2 1045.94  1066.1 1039.22  1313.5 1039.29    1346 1037.06
  1353.1 1035.29    1363 1037.01  1382.8 1045.55  1402.5 1048.93  1442.1  1059.9
  1531.2 1089.14  1590.9 1105.26    1770 1140.44  1909.4 1173.81  1929.2 1176.02
#Mann= 3 , 0 , 0
       0     .05       0    1346    .045       0    1363      .1       0
#XS Ineff= 2 , 0
         1023.77 1045.98
Permanent Ineff=
       F       F
Bank Sta=1346,1363
XS Rating Curve= 0 ,0
Exp/Cntr=0.3,0.1

Type RM Length L Ch R = 1 ,8968.8  ,548.8,547.3,543.3
XS GIS Cut Line= 4
     1725041.935        429518.9     1725478.692      428966.395
     1725699.564      428826.156     1726428.654      428477.233
#Sta/Elev= 30
       0 1114.76     119 1103.55   198.4 1083.48   238.1  1081.2   297.6 1070.57
   347.2  1064.4   376.9 1063.46   426.5 1065.39   565.4 1052.41   694.4 1044.49
     840 1042.35   898.1 1039.36   936.8 1041.11   946.5 1040.14   958.4 1036.38
   965.9 1034.44   975.9 1035.68   985.9  1038.1  1125.6 1038.79  1205.4 1046.62
  1265.3 1047.84    1405 1067.38  1454.9 1077.38  1504.8 1090.12  1624.5 1124.88
  1674.4 1130.49  1684.4 1134.04  1704.4 1146.11  1714.3 1150.19  1774.2 1166.73
#Mann= 3 , 0 , 0
       0     .05       0   958.4    .045       0   975.9     .05       0
#XS Ineff= 2 , 0
          936.45 1041.02
Permanent Ineff=
       F       F
Bank Sta=958.4,975.9
XS Rating Curve= 0 ,0
Exp/Cntr=0.3,0.1

Type RM Length L Ch R = 1 ,8421.5  ,46,46,46
XS GIS Cut Line= 4
     1725725.529      429468.987     1726018.497      429269.334
     1726090.112      429217.251     1726354.869      429039.299
#Sta/Elev= 30
       0 1103.36     9.8  1099.8    59.1 1077.12    88.6 1066.24   108.3 1058.18
   118.2  1055.9   147.7 1051.95   157.6 1049.57   187.1 1040.71     197 1039.34
   275.8 1035.55     325 1035.92   344.7 1037.37   354.5 1037.47   364.4 1037.28
   374.2 1035.25     384 1034.37   390.1 1035.44   433.2 1039.88     483 1049.87
   532.8 1056.14   552.7 1058.02   572.7 1062.26   602.6 1071.47   612.6 1075.14
   632.5 1084.48   662.4  1095.8   702.3 1107.13   742.2 1119.98   762.1 1127.06
#Mann= 3 , 0 , 0
       0     .05       0   374.2    .045       0   390.1     .05       0
Bank Sta=374.2,390.1
XS Rating Curve= 0 ,0
Exp/Cntr=0.3,0.1

Type RM Length L Ch R = 1 ,8375.5  ,433.7,433.2,432.6
XS GIS Cut Line= 4
     1725732.039       429521.07     1726025.008      429321.417
     1726096.622      429269.334     1726361.379      429091.383
#Sta/Elev= 30
       0  1107.8    19.7 1100.53    49.2 1085.66    68.9 1078.11     128 1063.96
   147.7 1057.68   167.4 1054.67     197 1042.22   206.8 1038.95   226.5 1037.18
   295.4 1035.23   354.5 1035.68   374.2 1037.31   393.9 1037.23   402.3 1034.98
   413.6 1034.29   417.3 1034.87   443.1 1037.84     453  1040.1     483 1051.09
   502.9 1056.07   522.8 1058.77   582.6  1062.5   602.6 1064.66   612.6  1067.4
   632.5 1068.93   672.4 1079.84   702.3 1091.12   722.2    1097   762.1 1101.36
#Mann= 3 , 0 , 0
       0     .05       0   402.3    .045       0   417.3     .05       0
Bank Sta=402.3,417.3
XS Rating Curve= 0 ,0
Exp/Cntr=0.3,0.1

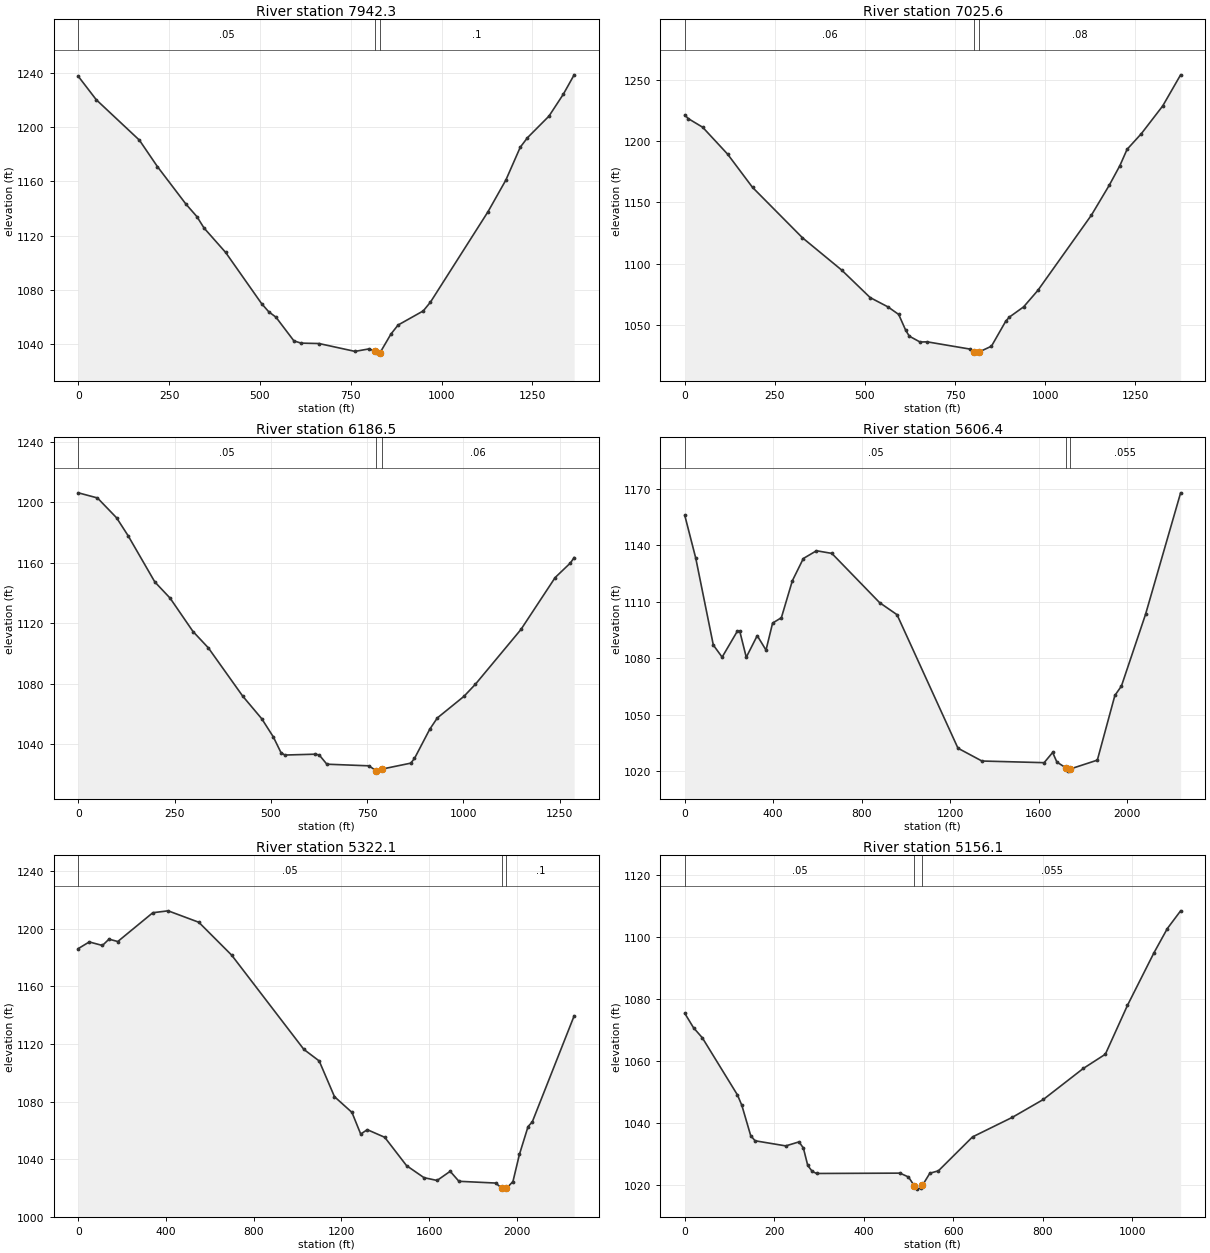
Type RM Length L Ch R = 1 ,7942.3  ,933.4,916.7,898.7
XS GIS Cut Line= 3
     1725689.189      430138.567     1726224.077      429714.692
     1726766.411       429300.14
#Sta/Elev= 30
       0 1237.63    49.4 1220.35   168.2 1190.46   217.6 1170.99   296.7 1143.07
   326.4 1133.98   346.2  1125.5   405.5 1107.51   504.4 1069.72   524.2 1063.63
     544 1059.66   593.5 1042.13   613.2 1040.45   662.7 1040.15   761.6 1034.35
   801.2 1036.22   815.9 1034.49     821 1033.06   830.9 1033.46   860.6 1047.14
   880.3 1053.82   949.6 1064.26   969.4 1070.73  1127.7  1137.5  1177.1 1161.01
  1216.7 1185.25  1236.5 1192.27  1295.8 1208.26  1335.4  1224.5  1365.1 1238.77
#Mann= 3 , 0 , 0
       0     .05       0   815.9    .045       0   830.9      .1       0
Bank Sta=815.9,830.9
XS Rating Curve= 0 ,0
Exp/Cntr=0.3,0.1

Type RM Length L Ch R = 1 ,7025.6  ,835.8,839.1,842.4
XS GIS Cut Line= 3
     1726984.407      430966.224     1726988.421      430283.744
     1727105.813      429600.485
#Sta/Elev= 30
       0 1221.39     9.9 1218.43    49.5 1211.44   118.7 1189.46   187.9 1162.26
   326.4 1121.08   435.2 1094.68   514.3 1072.17   563.8 1064.54   593.5 1058.38
   613.2 1045.28   623.1 1040.59   652.8 1035.84   672.6 1035.98   791.4 1030.05
     802  1027.4   811.2 1026.75     817 1027.77   850.9 1032.41   890.5 1052.82
   900.4 1056.17     940 1064.53   979.6 1078.01  1128.2 1139.54  1177.7 1163.97
  1207.4 1180.13  1227.2 1193.34  1266.8 1206.16  1326.2 1228.88  1375.8 1254.27
#Mann= 3 , 0 , 0
       0     .06       0     802    .045       0     817     .08       0
Bank Sta=802,817
XS Rating Curve= 0 ,0
Exp/Cntr=0.3,0.1

Type RM Length L Ch R = 1 ,6186.5  ,584.1,580,556.1
XS GIS Cut Line= 3
     1727493.785      431160.585     1727744.545      430470.075
     1727921.709      429946.417
#Sta/Elev= 30
       0 1206.23    49.6 1202.85    99.3 1189.73   129.1 1177.94   198.6 1147.32
   238.3  1136.6   297.8 1114.53   337.5 1103.76   426.9  1071.8   476.5 1056.79
   506.3 1044.85   526.2 1034.47   536.1 1032.88   615.5 1033.44   625.4 1032.94
   645.3 1026.82   754.4 1025.75   772.6 1022.65   774.1 1022.24   787.6 1023.55
     863 1027.51   872.8 1030.62   912.3 1049.88   932.1  1057.4  1001.2 1071.66
  1030.8 1079.63  1149.2 1115.88  1238.1 1150.23  1277.6 1159.85  1287.4 1163.44
#Mann= 3 , 0 , 0
       0     .05       0   772.6    .045       0   787.6     .06       0
Bank Sta=772.6,787.6
XS Rating Curve= 0 ,0
Exp/Cntr=0.3,0.1

Type RM Length L Ch R = 1 ,5606.4  ,289.4,284.3,278.7
XS GIS Cut Line= 6
     1727248.586      431953.979     1727641.308      431417.181
     1727856.605      431161.695     1728201.657      430627.841
     1728229.869      430408.657      1728245.06      430022.372
#Sta/Elev= 30
       0 1155.92    49.6  1133.2     129 1086.99   168.8 1080.55   238.2 1094.48
   248.2 1094.53     278 1080.48   327.6 1091.99   367.3  1084.3   397.1 1098.68
   436.8 1101.53   486.4 1121.18   536.1 1133.03   595.6 1137.16   665.1 1135.75
   881.3 1109.53   959.9 1103.13  1235.5  1032.1  1343.8 1025.28  1625.2  1024.4
  1663.7 1029.84  1682.9 1024.71  1725.4 1021.51    1731  1019.9  1740.4 1020.93
  1865.8 1025.75  1945.1 1060.16  1974.8 1065.18  2083.9 1103.35  2242.5 1167.98
#Mann= 3 , 0 , 0
       0     .05       0  1725.4    .045       0  1740.4    .055       0
#XS Ineff= 2 , 0
         1663.53  1029.8
Permanent Ineff=
       F       F
Bank Sta=1725.4,1740.4
XS Rating Curve= 0 ,0
Exp/Cntr=0.3,0.1

Type RM Length L Ch R = 1 ,5322.1  ,157.6,166,174.4
XS GIS Cut Line= 6
      1728519.42      432308.145     1728517.866      431488.695
     1728516.327      430990.254     1728459.904      430525.845
      1728401.31      430256.747     1728366.588      430059.265
#Sta/Elev= 30
       0 1186.31      50  1190.9   109.9 1188.44   139.9 1192.83   179.9 1191.18
   339.8 1211.19   409.7  1212.5   549.6 1204.55   699.5 1181.71  1028.8 1116.26
  1098.6 1108.26  1168.4 1083.44  1248.1 1072.52    1288 1057.48  1317.9 1060.54
  1397.5 1055.25  1497.1 1035.57  1576.7 1027.21  1636.4 1025.27  1696.1 1031.62
    1736 1024.69  1903.8 1023.47  1932.3 1019.77  1943.1 1019.25  1952.9 1019.77
  1982.4 1024.52  2011.9 1043.33  2051.3 1062.68  2070.7 1065.98  2261.6 1139.59
#Mann= 3 , 0 , 0
       0     .05       0  1932.3    .045       0  1952.9      .1       0
#XS Ineff= 2 , 0
         1695.51 1031.51
Permanent Ineff=
       F       F
Bank Sta=1932.3,1952.9
XS Rating Curve= 0 ,0
Exp/Cntr=0.3,0.1

Type RM Length L Ch R = 1 ,5156.1  ,57.2,58.9,64.2
XS GIS Cut Line= 4
     1728603.133      430868.726     1728570.581      430389.126
     1728613.984      430232.876     1728815.806      429814.039
#Sta/Elev= 30
       0 1075.32    19.6 1070.65    39.2 1067.42   117.7 1048.94   127.5 1045.57
   147.2 1035.82     157 1034.14   225.6 1032.48   255.1 1033.78   264.9 1031.81
   274.7 1026.17   284.5 1024.28   294.3 1023.57   480.7 1023.68   499.8 1022.43
  512.971019.536   518.9 1018.51   528.4    1019   530.9 1019.72   547.5 1023.65
   566.6 1024.42   642.9 1035.39   731.9 1041.72   801.1 1047.49   890.2  1057.5
   939.6 1062.11   989.1 1077.93  1048.4 1094.94  1078.1 1102.73  1107.8 1108.46
#Mann= 3 , 0 , 0
       0     .05       0  512.97    .045       0   530.9    .055       0
Bank Sta=512.97,530.9
XS Rating Curve= 0 ,0
Exp/Cntr=0.3,0.1

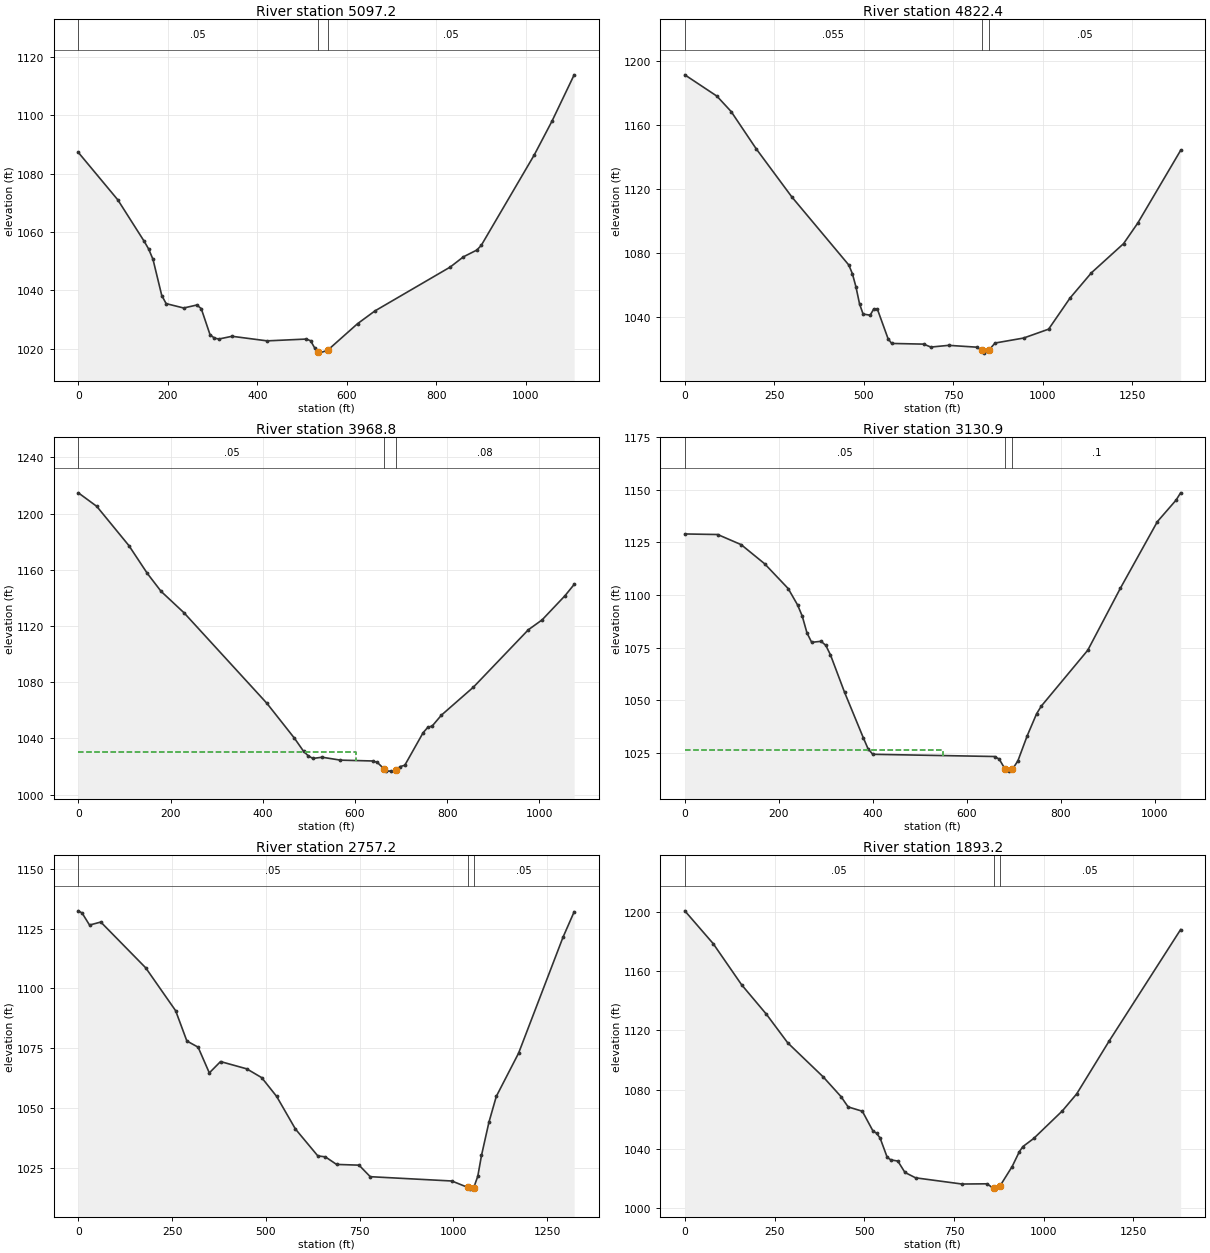
Type RM Length L Ch R = 1 ,5097.2  ,281.9,274.8,264
XS GIS Cut Line= 4
     1728653.046      430883.917     1728620.494      430404.317
     1728663.897      430248.067      1728865.72       429829.23
#Sta/Elev= 30
       0 1087.28    88.3 1071.01   147.2 1056.81     157 1054.22   166.8 1050.65
   186.4 1038.26   196.2 1035.48   235.4 1033.98   264.9 1035.01   274.7 1033.74
   294.3 1024.82   304.1 1023.67   313.9 1023.35   343.4 1024.29   421.8 1022.72
   509.3 1023.34   518.9 1022.76   528.4 1020.21     5351019.036   537.9 1018.52
     557  1019.5   623.8  1028.6   662.6 1032.97   830.8    1048   860.5 1051.52
   890.2 1053.82   900.1  1055.4  1018.8 1086.46  1058.3    1098  1107.8 1113.86
#Mann= 3 , 0 , 0
       0     .05       0     535    .045       0     557     .05       0
Bank Sta=535,557
XS Rating Curve= 0 ,0
Exp/Cntr=0.3,0.1

Type RM Length L Ch R = 1 ,4822.4  ,845.2,853.6,860.3
XS GIS Cut Line= 3
     1728989.915      431142.067     1728901.112      430440.225
      1728922.29      429762.457
#Sta/Elev= 30
       0 1191.32    89.7 1178.03   129.5 1168.41   199.3 1145.21   298.9 1115.15
   458.3 1072.59   468.3 1067.17   478.3 1058.94   488.2 1048.43   498.2 1041.99
   518.1 1041.27   528.1 1045.22     538 1045.14   567.9 1026.66   577.9 1023.64
   667.6 1023.21   687.5 1021.37   737.4 1022.45   817.1 1021.29  829.121019.361
   837.1 1017.59  848.861019.287     867 1023.89   946.8 1027.01  1016.6 1032.55
  1076.4 1051.96  1136.2 1067.73    1226 1085.93  1265.9 1098.83  1385.5 1144.16
#Mann= 3 , 0 , 0
       0    .055       0  829.12    .045       0  848.86     .05       0
Bank Sta=829.12,848.86
XS Rating Curve= 0 ,0
Exp/Cntr=0.3,0.1

Type RM Length L Ch R = 1 ,3968.8  ,847.9,837.9,827.3
XS GIS Cut Line= 3
     1729409.558      431264.058     1729657.317      430632.716
     1729795.461      430260.402
#Sta/Elev= 30
       0 1214.81    39.9  1205.2   109.7 1177.24   149.6 1157.46   179.5 1144.67
   229.4 1129.36   408.9 1065.01   468.8  1040.1   488.7 1030.73   498.7  1027.6
   508.7 1025.73   528.6 1026.62   568.5 1024.54   638.3 1023.94   648.3 1022.96
  663.931018.022   668.2 1016.81   678.2 1016.72   688.1 1017.28   698.1 1019.97
     708  1020.9   747.7 1044.04   757.6 1047.78   767.6 1048.91   787.4 1056.56
   856.9 1076.52     976 1117.36  1005.8 1124.38  1055.5 1141.61  1075.3 1149.62
#Mann= 3 , 0 , 0
       0     .05       0  663.93    .045       0   688.1     .08       0
#XS Ineff= 2 , 0
          602.54 1030.41
Permanent Ineff=
       F       F
Bank Sta=663.93,688.1
XS Rating Curve= 0 ,0
Exp/Cntr=0.3,0.1

Type RM Length L Ch R = 1 ,3130.9  ,383.9,373.7,363.9
XS GIS Cut Line= 4
     1730527.051      431277.648     1730471.496      430770.703
     1730445.888      430503.342     1730365.593      430238.585
#Sta/Elev= 30
       0 1129.03      70 1128.76     120 1123.94     170 1114.84     220 1103.07
     240 1095.29     250 1089.95     260 1081.99     270 1077.51     290    1078
     300 1076.08     310 1071.55     340 1053.76     380 1032.08     390 1026.91
     400 1024.28   659.2 1023.23   669.1    1022   681.9 1017.15     689 1016.28
   696.9 1017.06   708.9 1021.17   728.8 1033.14   748.7 1043.56   758.7 1047.19
   857.6 1073.76   926.8 1103.15  1005.8 1134.91  1045.4 1145.09  1055.2 1148.58
#Mann= 3 , 0 , 0
       0     .05       0   681.9    .045       0   696.9      .1       0
#XS Ineff= 2 , 0
          549.26 1026.19
Permanent Ineff=
       F       F
Bank Sta=681.9,696.9
XS Rating Curve= 0 ,0
Exp/Cntr=0.3,0.1

Type RM Length L Ch R = 1 ,2757.2  ,860,864.1,867.3
XS GIS Cut Line= 3
     1731195.581      431285.827     1730826.724      430589.038
     1730552.406      430131.062
#Sta/Elev= 30
       0 1132.41      10  1131.5    29.9 1126.46    59.9 1127.72   179.6  1108.6
   259.5 1090.66   289.4    1078   319.4 1075.42   349.3 1064.66   379.2  1069.4
   449.1 1066.36     489 1062.68   528.9 1054.82   578.8 1041.23   638.7 1029.96
   658.7 1029.57   688.6 1026.41   748.5  1026.1   778.4 1021.28     996 1019.48
    1039 1016.77  1045.4 1016.08    1054  1016.5  1065.2 1021.46  1075.1 1030.17
  1094.9 1044.03  1114.6 1054.85    1174 1072.91  1292.6 1121.43  1322.2 1132.01
#Mann= 3 , 0 , 0
       0     .05       0    1039    .045       0    1054     .05       0
Bank Sta=1039,1054
XS Rating Curve= 0 ,0
Exp/Cntr=0.3,0.1

Type RM Length L Ch R = 1 ,1893.2  ,1093.3,1084.1,1070.9
XS GIS Cut Line= 3
     1731698.292      430791.307     1731435.825      430139.917
      1731186.01      429508.537
#Sta/Elev= 30
       0  1200.7    79.1 1178.56   158.3 1150.79   227.5 1130.87   286.8 1111.59
   385.8 1088.57   435.2 1075.32     455 1068.36   494.6 1065.44   524.2 1052.12
   534.1 1050.63     544 1047.39   563.8 1034.38   573.7 1032.63   593.5 1031.81
   613.3 1024.14   642.9  1020.5   772.2 1016.31   842.1 1016.46  860.291013.304
     862 1012.87   877.4 1014.73     912 1028.13   931.9 1038.11   941.9 1041.59
   971.9 1047.04  1051.8 1065.68  1091.7 1077.13  1181.6  1112.6  1381.3 1188.06
#Mann= 3 , 0 , 0
       0     .05       0  860.29    .045       0   877.4     .05       0
Bank Sta=860.29,877.4
XS Rating Curve= 0 ,0
Exp/Cntr=0.3,0.1

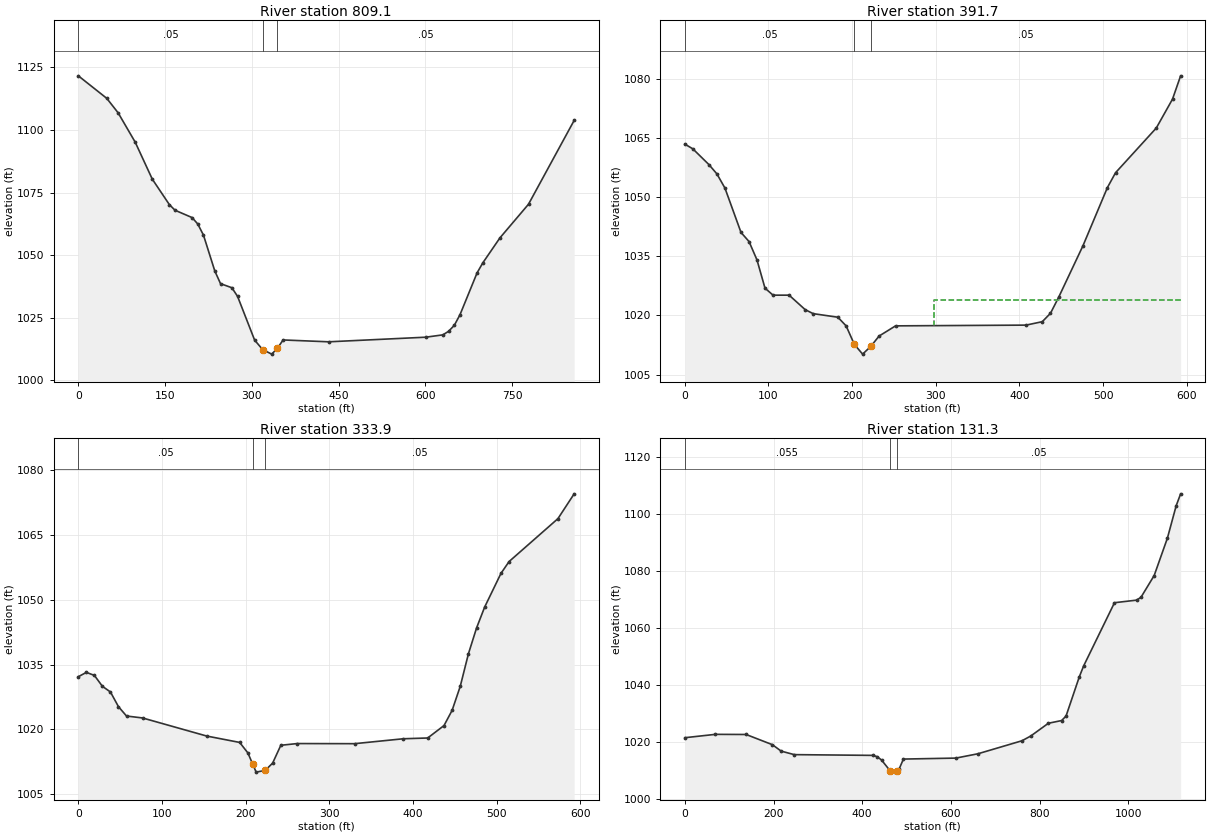
Type RM Length L Ch R = 1 ,809.1   ,432,417.4,402.8
XS GIS Cut Line= 3
     1732347.925      429867.858      1732051.05      429610.046
     1731696.883      429310.567
#Sta/Elev= 30
       0 1121.63    49.2 1112.63    68.8 1106.85    98.3 1095.14   127.8 1080.39
   157.3 1070.22   167.1 1067.96   196.6 1065.03   206.4 1062.48   216.3 1058.02
   235.9 1043.69   245.8 1038.64   265.4 1037.01   275.2 1033.57   304.7  1016.1
   318.7 1012.29   334.2  1010.5     344 1012.79   353.9 1016.16   432.7 1015.42
   600.4 1017.26     630 1018.19   639.9  1019.6   649.8 1021.99   659.6 1026.19
   689.2 1042.94   699.1 1046.94   728.7 1056.92   778.1 1070.36     857 1103.83
#Mann= 3 , 0 , 0
       0     .05       0   318.7    .045       0     344     .05       0
Bank Sta=318.7,344
XS Rating Curve= 0 ,0
Exp/Cntr=0.3,0.1

Type RM Length L Ch R = 1 ,391.7   ,57.8,57.8,57.8
XS GIS Cut Line= 4
      1732439.07      429302.754     1732290.633      429263.692
     1732163.029      429253.275     1731866.154      429159.525
#Sta/Elev= 30
       0 1063.46     9.6 1062.26    28.8 1058.27    38.4  1055.9      48  1052.3
    67.2 1041.05    76.8 1038.74    86.3 1034.08    95.9 1026.91   105.5 1025.14
   124.7 1025.14   143.9 1021.47   153.5 1020.45     183 1019.54   192.9 1017.34
   202.7 1012.65   212.6 1010.18   222.4 1012.15   232.3 1014.77     252 1017.35
     408 1017.54   427.4 1018.41   437.2 1020.54   446.9 1024.57   476.1  1037.7
   505.3 1052.45     515  1056.2   563.7 1067.54   583.1 1074.87   592.8 1080.78
#Mann= 3 , 0 , 0
       0     .05       0   202.7    .045       0   222.4     .05       0
#XS Ineff= 2 , 0
                          297.99         1023.94
Permanent Ineff=
       F       F
Bank Sta=202.7,222.4
XS Rating Curve= 0 ,0
Exp/Cntr=0.3,0.1

Type RM Length L Ch R = 1 ,333.9   ,196.6,202.6,208.5
XS GIS Cut Line= 4
     1732441.675      429245.463     1732293.237        429206.4
     1732165.633      429195.983     1731868.758      429102.233
#Sta/Elev= 30
       0 1032.18     9.6 1033.18    19.2 1032.48    28.8 1029.95    38.4 1028.64
      48 1025.23    57.6 1023.07    76.8 1022.62   153.5 1018.43   192.9 1016.95
   202.7 1014.52   208.5 1011.91   212.6 1010.07   223.5 1010.48   232.3 1012.16
   242.1 1016.29   261.8 1016.69   330.2 1016.66   388.5  1017.8   417.7 1017.98
   437.2 1020.86   446.9 1024.39   456.6 1029.94   466.4  1037.5   476.1 1043.46
   485.8 1048.32   505.3 1056.12     515 1058.86   573.4  1068.8   592.8 1074.55
#Mann= 3 , 0 , 0
       0     .05       0   208.5    .045       0   223.5     .05       0
Bank Sta=208.5,223.5
XS Rating Curve= 0 ,0
Exp/Cntr=0.3,0.1

Type RM Length L Ch R = 1 ,131.3   ,138.4,131.3,124
XS GIS Cut Line= 4
     1732670.841      429219.421     1732420.841      429060.567
     1732152.612      428964.213     1731616.154      428964.213
#Sta/Elev= 30
       0  1021.6    69.1 1022.78   138.2 1022.73   197.5 1019.16   217.2 1016.91
   246.8 1015.68     424 1015.42   433.8 1014.96   443.6 1013.78   462.5 1010.09
   473.1 1009.56   477.5 1010.01   482.9 1010.56   492.8 1014.13     611 1014.47
   660.7 1015.98     760 1020.53   779.9  1022.2   819.6 1026.66   849.4 1027.61
   859.4 1029.17   889.2 1042.86   899.1 1046.73   968.6 1068.84  1018.3 1069.74
  1028.3 1070.73  1058.1 1078.36  1087.9 1091.43  1107.7 1102.78  1117.7 1106.94
#Mann= 3 , 0 , 0
       0    .055       0   462.5    .045       0   477.5     .05       0
Bank Sta=462.5,477.5
XS Rating Curve= 0 ,0
Exp/Cntr=0.3,0.1

Chan Stop Cuts=-1
Use User Specified Reach Order=0
Composite Channel Slope=5